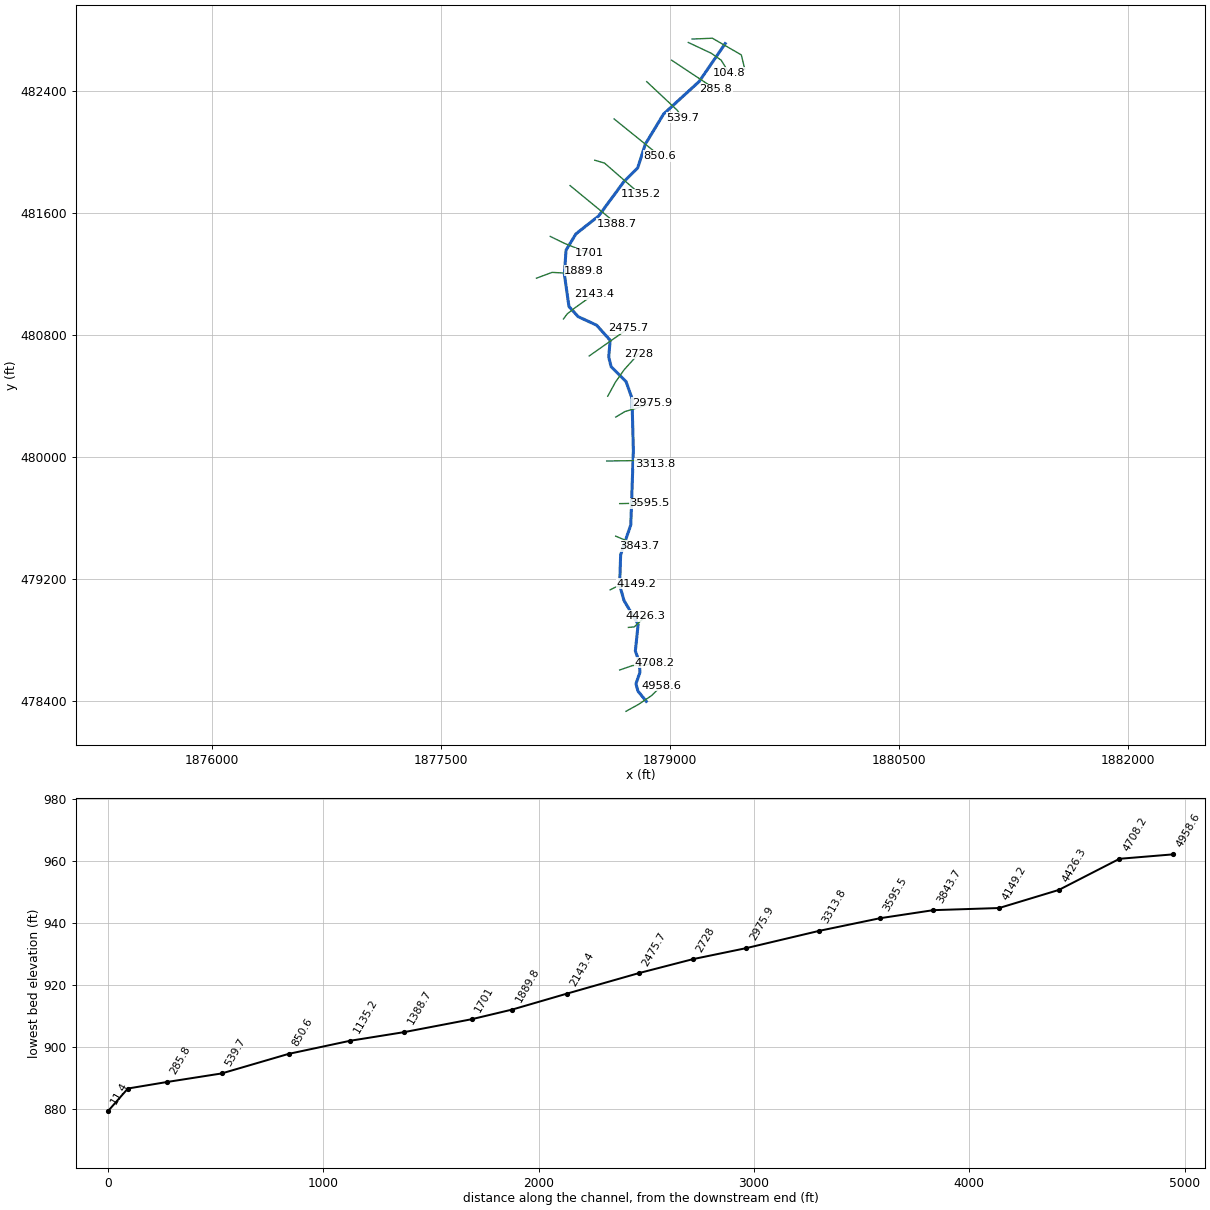
--- PONDFORK.prj (project) ---

Proj Title=PONDFORK
Current Plan=p01
Default Exp/Contr=0,0
English Units
Geom File=g01
Flow File=f01
Plan File=p01
BEGIN DESCRIPTION:
END DESCRIPTION:
DSS Export Rating Curves= 0
DSS Export Rating Curve Sorted= 0
DSS Export Volume Flow Curves= 0
DXF OffsetX= 0
DXF OffsetY= 0
DXF ScaleX= 0
DXF ScaleY= 0

--- PONDFORK.p01 (plan) ---

Plan Title=Floodplain
Program Version=4.00
Geom File=g01
Flow File=f01
K Sum by GR=0
Std Step Tol=0.01
Critical Tol=0.01
Num of Std Step Trials=20
Max Error Tol=0.3
Flow Tol Ratio=0.001
Split Flow NTrial=30
Split Flow Tol=0.02
Split Flow Ratio=0.02
Log Output Level=0
Friction Slope Method=1
Unsteady Friction Slope Method=2
Unsteady Bridges Friction Slope Method=1
Global Log Level=0
CheckData=False
Run HTab=0
Run UNet=0
Run PostProcess=0
UNET Theta=0
UNET Theta Warmup=0
UNET ZTol=0
UNET ZSATol=0
UNET MxIter=0
UNET MaxInSteps=0
UNET DtIC=0
UNET DtMin=0
UNET MaxCRTS=0
UNET WFStab=0
UNET SFStab=0
UNET WFX=0
UNET SFX=0
UNET DSS MLevel=0
UNET DZMax Abort=0
UNET Convert EG Bridges=0
UNET Use Existing IB Tables=0
UNET Froude Limit=0
UNET Froude Power=0
Write IC File=0
Echo Input=False
Echo Output=False
Write Detailed=0

--- PONDFORK.f01 (steady flow) ---

Flow Title=NFF Regression Equation
Program Version=4.10
Number of Profiles= 1
Profile Names=P100yr
River Rch & RM=PONDFORK,Main            ,4958.6
855.0181
River Rch & RM=PONDFORK,Main            ,4708.2
936.5103
River Rch & RM=PONDFORK,Main            ,1388.7
1068.103
Boundary for River Rch & Prof#=PONDFORK,Main            , 1
Up Type= 0
Dn Type= 3
Dn Slope=0.05
DSS Import GetInterval= 0
DSS Import GetPeak= 0
DSS Import FillOption= 0

--- PONDFORK.g01 (geometry) ---

Geom Title=USGS 10m DEM
Program Version=4.10

River Reach=PONDFORK        ,Main
Reach XY= 30
     1878846.837      478395.192     1878792.149      478462.901
     1878779.128      478511.078      1878805.17      478585.297
     1878801.264      478653.005     1878775.222      478725.922
     1878793.451      478900.401     1878701.003      479056.651
     1878672.358      479158.213     1878678.868      479357.432
     1878745.274      479554.047     1878762.201      480039.724
     1878753.087      480384.776     1878714.024      480494.151
     1878616.368      480591.807     1878600.743      480654.307
     1878610.154      480764.885     1878521.316      480863.942
     1878400.222      480919.932     1878340.326      480986.338
     1878310.254      481198.438     1878321.323      481356.487
     1878385.899      481462.901     1878534.337      481580.088
     1878701.084      481806.932     1878790.847      481896.494
     1878840.326      482051.442     1878960.118      482249.359
     1879193.191      482462.901     1879363.764      482711.599

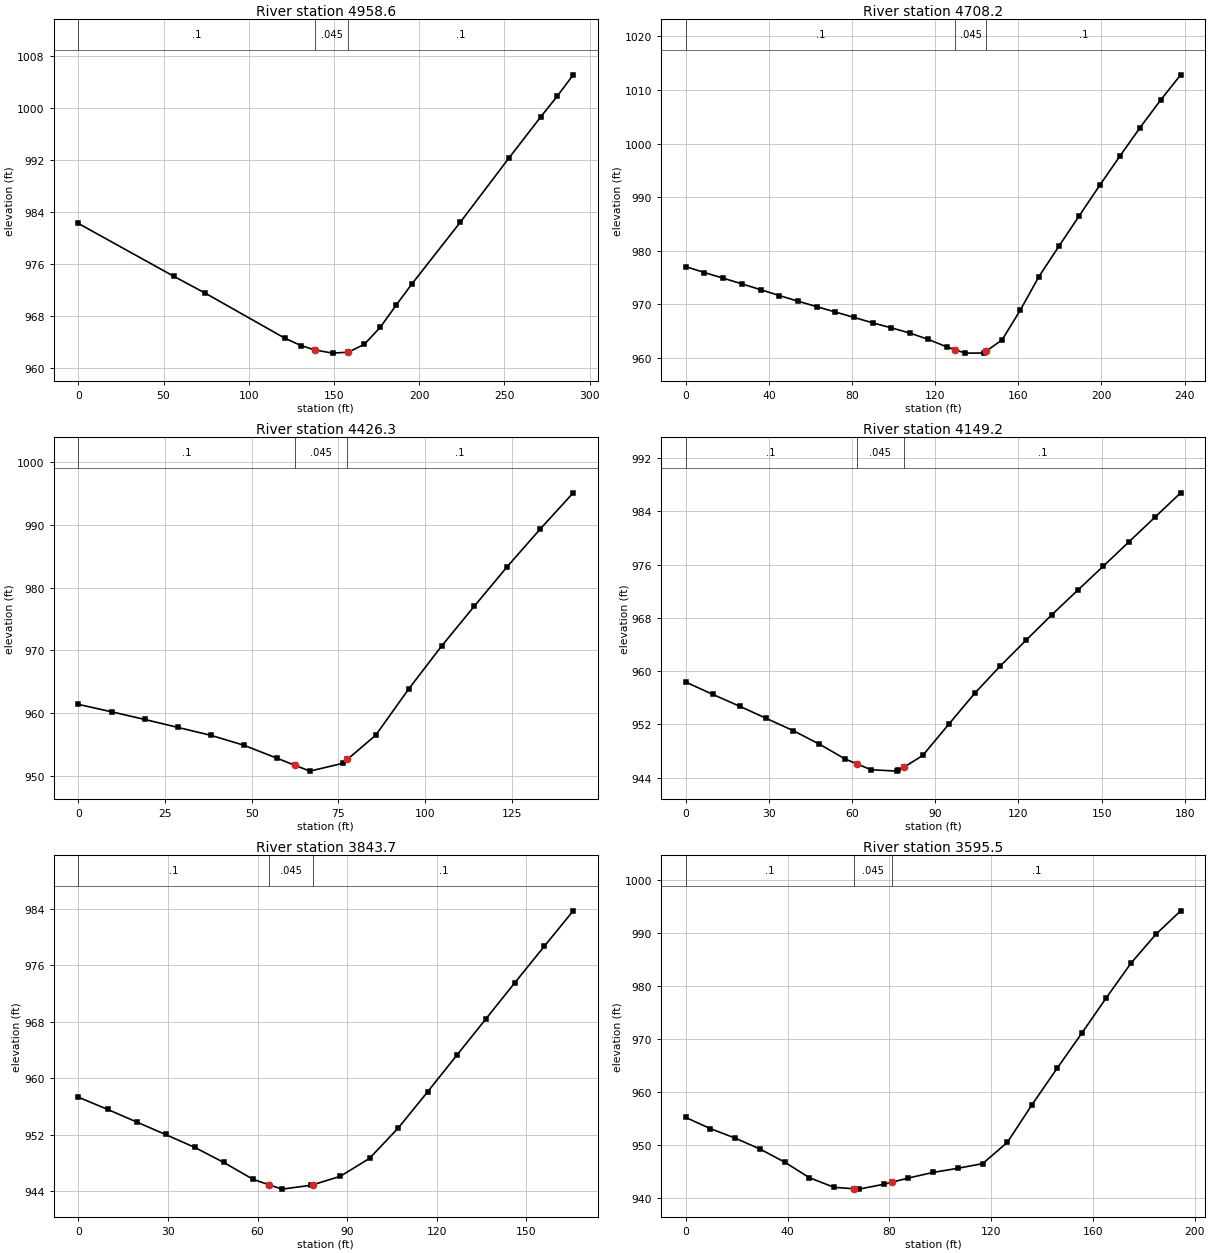
Type RM Length L Ch R = 1 ,4958.6  ,263.4,250.5,237.3
XS GIS Cut Line= 4
     1878714.111      478330.175     1878795.708      478375.314
     1878880.778      478432.606     1878948.486      478498.578
#Sta/Elev= 17
       0  982.24      56  974.12    74.6  971.51   121.2   964.6   130.6  963.48
   138.6  962.81   149.2  962.31   158.5  962.46   167.8  963.66   177.2  966.28
   186.5  969.68   195.8  972.96   224.2  982.44   252.5  992.22   271.4  998.63
   280.9 1001.75   290.4 1005.07
#Mann= 3 , 0 , 0
       0      .1       0   138.6    .045       0   158.5      .1       0
Bank Sta=138.6,158.5
XS Rating Curve= 0 ,0
Exp/Cntr=0.3,0.1

Type RM Length L Ch R = 1 ,4708.2  ,261.4,281.8,298.3
XS GIS Cut Line= 4
     1878672.444      478601.008     1878757.514      478630.522
     1878837.375      478632.258     1878903.347      478649.619
#Sta/Elev= 29
       0  977.02       9  975.91      18  974.86      27   973.8      36  972.72
      45  971.62      54  970.56      63  969.55      72  968.54      81  967.53
      90  966.52    98.9  965.59   107.8  964.62   116.7  963.43   125.6  962.03
   129.5  961.52   134.4  960.87   143.3  960.89   144.5  961.22   152.2  963.35
     161  968.92   169.9  975.15   179.7  980.92   189.4  986.56   199.2  992.22
   208.9  997.66   218.6 1002.98   228.4 1008.08   238.1 1012.82
#Mann= 3 , 0 , 0
       0      .1       0   129.5    .045       0   144.5      .1       0
Bank Sta=129.5,144.5
XS Rating Curve= 0 ,0
Exp/Cntr=0.3,0.1

Type RM Length L Ch R = 1 ,4426.3  ,291,277.1,266.1
XS GIS Cut Line= 3
     1878729.736      478880.522      1878767.93      478883.994
     1878844.319      478955.175
#Sta/Elev= 18
       0  961.43     9.6  960.25    19.2  959.03    28.8  957.76    38.4  956.49
    47.8  954.93    57.3  952.88    62.6  951.73    66.8  950.82    76.3  952.06
    77.6  952.67    85.8  956.52    95.3  963.85   104.8  970.68   114.3  977.06
   123.8  983.34   133.3  989.31   142.8  995.05
#Mann= 3 , 0 , 0
       0      .1       0    62.6    .045       0    77.6      .1       0
Bank Sta=62.6,77.6
XS Rating Curve= 0 ,0
Exp/Cntr=0.3,0.1

Type RM Length L Ch R = 1 ,4149.2  ,320.8,305.5,290.1
XS GIS Cut Line= 4
     1878609.944       479127.05     1878644.667      479144.411
     1878698.486      479160.036     1878781.819      479166.981
#Sta/Elev= 23
       0  958.36     9.7  956.52    19.4  954.74    29.1   952.9    38.8  951.06
    48.2  949.04    57.5  946.81    61.6   946.1    66.8   945.2    76.2  944.99
    76.6  945.09   78.83  945.61    85.5  947.35    94.9  952.05   104.2  956.66
   113.4  960.76   122.7  964.63     132  968.45   141.3  972.12   150.6  975.76
   159.9  979.43   169.2   983.1   178.5  986.77
#Mann= 3 , 0 , 0
       0      .1       0    61.6    .045       0   78.83      .1       0
Bank Sta=61.6,78.83
XS Rating Curve= 0 ,0
Exp/Cntr=0.3,0.1

Type RM Length L Ch R = 1 ,3843.7  ,238.5,248.3,257.5
XS GIS Cut Line= 2
     1878646.403      479479.481      1878799.18      479415.244
#Sta/Elev= 20
       0  957.33     9.8   955.6    19.5  953.82    29.2  952.04      39  950.21
    48.7  948.08    58.5  945.69    63.7  944.94    68.2   944.3      78  944.85
    78.7  944.94    87.7  946.11    97.5  948.66   107.2     953     117  958.11
   126.7  963.26   136.5  968.44   146.2  973.57     156   978.7   165.7  983.73
#Mann= 3 , 0 , 0
       0      .1       0    63.7    .045       0    78.7      .1       0
Bank Sta=63.7,78.7
XS Rating Curve= 0 ,0
Exp/Cntr=0.3,0.1

Type RM Length L Ch R = 1 ,3595.5  ,281.7,281.7,281.6
XS GIS Cut Line= 2
     1878672.444      479693.022     1878866.889      479696.494
#Sta/Elev= 23
       0  955.19     9.7  953.09    19.4  951.31    29.2  949.24    38.9  946.77
    48.6  943.84    58.3  942.03    66.1  941.76    68.1  941.69    77.8   942.6
    81.1     943    87.5  943.78    97.2  944.84     107  945.62   116.7   946.5
   126.4  950.51   136.1  957.61   145.9  964.43   155.6  971.04   165.3  977.76
     175  984.28   184.8  989.73   194.5  994.13
#Mann= 3 , 0 , 0
       0      .1       0    66.1    .045       0    81.1      .1       0
Bank Sta=66.1,81.1
XS Rating Curve= 0 ,0
Exp/Cntr=0.3,0.1

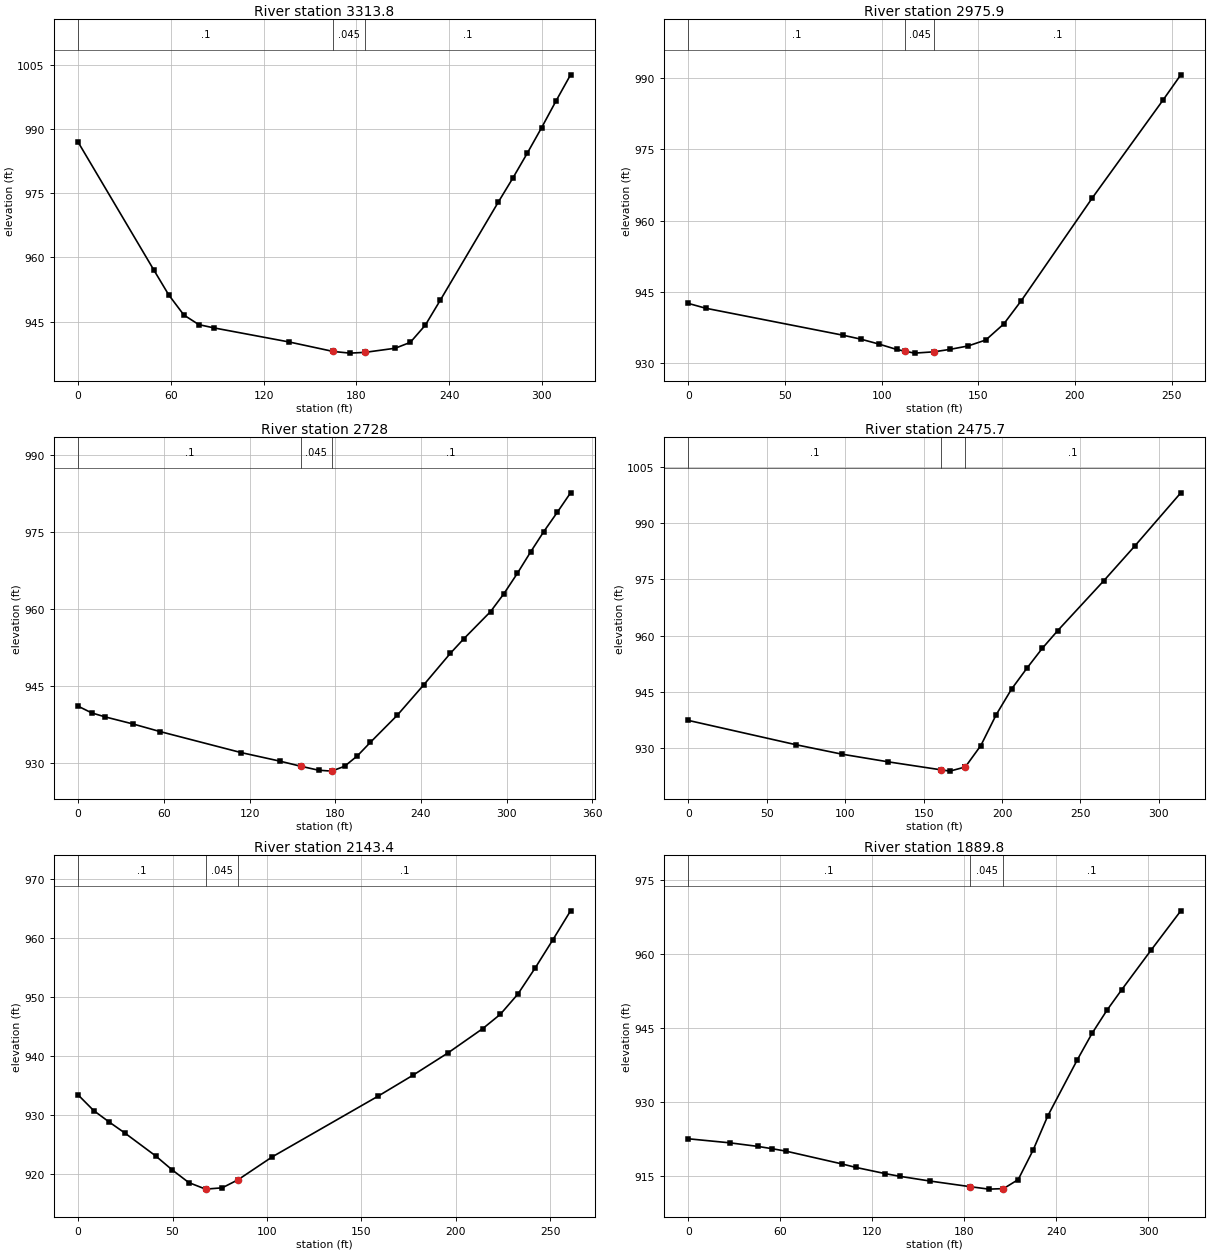
Type RM Length L Ch R = 1 ,3313.8  ,330.3,337.9,345.1
XS GIS Cut Line= 3
     1878587.375      479972.536      1878821.75      479976.008
     1878903.347      479955.175
#Sta/Elev= 20
       0  986.87    48.8  957.13    58.6  951.22    68.4  946.52    78.1  944.27
    87.9  943.51   136.7  940.21     165  938.01   175.8  937.62   185.6   937.8
   205.1  938.76   214.9  940.13   224.6  944.14   234.4  950.03   271.8  972.86
   281.2  978.46   290.5  984.25   299.9  990.29   309.3  996.58   318.6 1002.61
#Mann= 3 , 0 , 0
       0      .1       0     165    .045       0   185.6      .1       0
Bank Sta=165,185.6
XS Rating Curve= 0 ,0
Exp/Cntr=0.3,0.1

Type RM Length L Ch R = 1 ,2975.9  ,233.9,247.9,261.9
XS GIS Cut Line= 4
     1878646.403      480260.731     1878707.167      480297.189
     1878795.708      480323.231     1878882.514      480352.744
#Sta/Elev= 17
       0  942.54     8.9  941.53    80.1  935.83    89.3     935    98.6  933.97
   107.8  932.83   112.2  932.46     117  932.06   127.2  932.34   135.5  932.86
   144.7  933.57   153.9  934.83   163.2  938.21   172.3  943.14     209  964.78
   245.7  985.47   254.8  990.74
#Mann= 3 , 0 , 0
       0      .1       0   112.2    .045       0   127.2      .1       0
Bank Sta=112.2,127.2
XS Rating Curve= 0 ,0
Exp/Cntr=0.3,0.1

Type RM Length L Ch R = 1 ,2728    ,257.5,252.3,243.8
XS GIS Cut Line= 4
     1878594.319      480397.883     1878644.667      480489.897
     1878701.958      480571.494     1878795.708      480675.661
#Sta/Elev= 24
       0  941.12     9.5  939.82    19.1  939.03    38.1  937.69    57.2   936.2
     114  932.11   141.1  930.45   155.8  929.45   168.3  928.68   177.4   928.5
   186.5  929.44   195.5  931.48   204.6  934.11   223.3  939.34     242   945.3
   260.6  951.42     270  954.24   288.7  959.52     298  962.98   307.4  966.93
   316.7   971.1     326  975.09   335.4  978.82   344.7  982.61
#Mann= 3 , 0 , 0
       0      .1       0   155.8    .045       0   177.4      .1       0
Bank Sta=155.8,177.4
XS Rating Curve= 0 ,0
Exp/Cntr=0.3,0.1

Type RM Length L Ch R = 1 ,2475.7  ,332.6,332.4,333.1
XS GIS Cut Line= 2
     1878472.792      480661.772     1878729.736      480842.328
#Sta/Elev= 17
       0  937.47    68.7  930.99    98.1  928.47   127.6  926.43   161.2  924.31
   166.8  923.97   176.2  925.04   176.6  925.09   186.5  930.79   196.3     939
   206.1  945.83   215.9  951.39   225.7  956.68   235.5  961.37     265   974.7
   284.6  983.87     314  998.06
#Mann= 3 , 0 , 0
       0      .1       0   161.2    .045       0   176.2      .1       0
Bank Sta=161.2,176.2
XS Rating Curve= 0 ,0
Exp/Cntr=0.3,0.1

Type RM Length L Ch R = 1 ,2143.4  ,269.9,253.6,237
XS GIS Cut Line= 4
     1878304.389      480904.828     1878328.694      480937.814
     1878377.305      480976.008     1878505.778      481068.022
#Sta/Elev= 20
       0  933.34     8.2   930.7    16.4  928.76    24.6  926.92      41  923.02
    49.8  920.64    58.6  918.49    67.5  917.38    76.3   917.6    84.7  918.97
   102.8  922.85   158.6  933.09   177.2  936.66   195.8  940.45   214.3  944.59
   223.6  947.01   232.9  950.44   242.2  954.93   251.5  959.68   260.8  964.55
#Mann= 3 , 0 , 0
       0      .1       0    67.5    .045       0    84.7      .1       0
Bank Sta=67.5,84.7
XS Rating Curve= 0 ,0
Exp/Cntr=0.3,0.1

Type RM Length L Ch R = 1 ,1889.8  ,196.3,188.8,181.1
XS GIS Cut Line= 4
     1878127.305      481172.189     1878229.736      481210.383
     1878354.736      481203.439     1878439.805        481220.8
#Sta/Elev= 22
       0  922.48    27.3  921.65    45.6  920.92    54.7  920.46    63.8  919.96
   100.2  917.37   109.3  916.66   128.6  915.39   138.2  914.84   157.5   913.9
   183.8  912.75     196  912.25   205.6  912.35   215.2  914.19   224.9  920.16
   234.5  927.13   253.8  938.55   263.4  943.91   273.1   948.6   282.8   952.8
     302  960.86   321.3  968.81
#Mann= 3 , 0 , 0
       0      .1       0   183.8    .045       0   205.6      .1       0
Bank Sta=183.8,205.6
XS Rating Curve= 0 ,0
Exp/Cntr=0.3,0.1

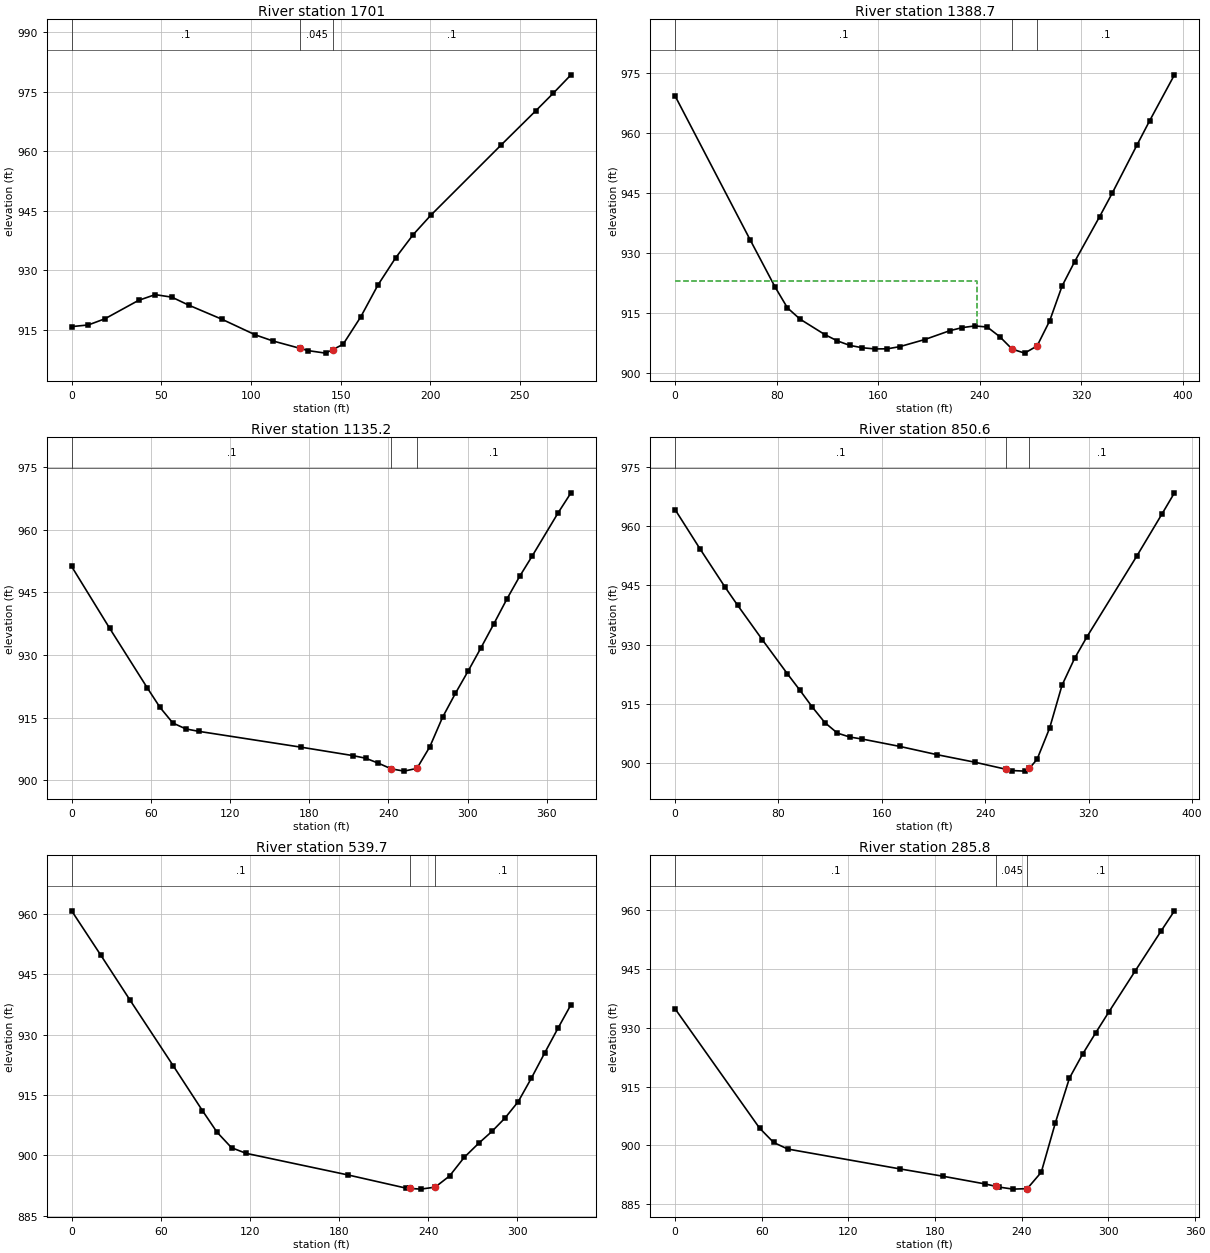
Type RM Length L Ch R = 1 ,1701    ,319.2,312.3,305.4
XS GIS Cut Line= 3
     1878217.583      481446.494     1878309.597      481401.356
     1878472.792      481335.383
#Sta/Elev= 24
       0   915.8     9.3  916.22    18.6  917.78    37.3  922.41    46.6  923.86
    55.9  923.22    65.2  921.23    83.8  917.66   102.5  913.71   112.3  912.18
   127.6   910.3   131.8  909.76   141.6  909.12  145.62     910   151.4  911.34
   161.2  918.21   170.9  926.33   180.7  933.13   190.5  938.98   200.3  943.85
   239.4   961.5     259  970.24   268.7  974.64   278.5  979.24
#Mann= 3 , 0 , 0
       0      .1       0   127.6    .045       0  145.62      .1       0
Bank Sta=127.6,145.62
XS Rating Curve= 0 ,0
Exp/Cntr=0.3,0.1

Type RM Length L Ch R = 1 ,1388.7  ,254.1,253.5,252.8
XS GIS Cut Line= 2
     1878347.792      481779.828     1878651.611      481529.828
#Sta/Elev= 29
       0  969.28      59  933.38    78.7  921.54    88.5  916.29    98.4  913.48
     118   909.6   127.9  908.02   137.7   906.9   147.6  906.31   157.4  906.02
   167.2  906.05     177  906.59   196.7  908.37   216.4  910.58   226.2  911.35
   236.1  911.77   245.9   911.5   255.8  909.08   265.5  905.98   275.4  904.97
   285.2  906.77   295.1  913.04   304.9  921.76   314.8  927.86   334.4  939.07
   344.3  944.92     364  957.08   373.8  963.04   393.4  974.56
#Mann= 3 , 0 , 0
       0      .1       0   265.5    .045       0   285.2      .1       0
#XS Ineff= 2 , 0
          237.73  923.06
Permanent Ineff=
       F       F
Bank Sta=265.5,285.2
XS Rating Curve= 0 ,0
Exp/Cntr=0.3,0.1

Type RM Length L Ch R = 1 ,1135.2  ,283.7,284.6,285.3
XS GIS Cut Line= 3
      1878509.25      481946.494     1878573.486      481927.397
     1878807.861      481722.536
#Sta/Elev= 25
       0   951.2    28.7  936.44    57.4  922.06      67   917.4    76.7  913.68
    86.5  912.27    96.2  911.69     174  907.88   212.9  905.88   222.7  905.25
   232.4  904.05   242.1   902.7   251.8  902.15   261.6  902.81   271.3  907.95
     281  915.05   290.8  920.82   300.5   926.2   310.2  931.76   319.9  937.47
   329.7  943.37   339.4  948.82   349.1   953.8   368.6  964.08   378.3  968.85
#Mann= 3 , 0 , 0
       0      .1       0   242.1    .045       0   261.6      .1       0
Bank Sta=242.1,261.6
XS Rating Curve= 0 ,0
Exp/Cntr=0.3,0.1

Type RM Length L Ch R = 1 ,850.6   ,312.6,310.9,309.4
XS GIS Cut Line= 2
     1878635.986      482217.328     1878936.333      481974.272
#Sta/Elev= 27
       0   964.2    19.3  954.24    38.6  944.58    48.3     940    67.6  931.18
    86.9  922.59    96.6  918.42   106.2  914.15   115.9  910.22   125.6  907.56
   135.2  906.57   144.9  906.05   173.9  904.19   202.8  902.09   231.8   900.2
   255.7  898.43   260.8  898.08   270.5  897.93  274.22  898.67   280.1  900.92
   289.8  908.82   299.4  919.69   309.1  926.48   318.8  932.02   357.4   952.5
   376.7  963.06   386.4  968.45
#Mann= 3 , 0 , 0
       0      .1       0   255.7    .045       0  274.22      .1       0
Bank Sta=255.7,274.22
XS Rating Curve= 0 ,0
Exp/Cntr=0.3,0.1

Type RM Length L Ch R = 1 ,539.7   ,249.8,254,257.4
XS GIS Cut Line= 3
     1878849.528      482462.119      1879049.18      482274.619
     1879085.639      482224.272
#Sta/Elev= 23
       0  960.81    19.6   949.8    39.1  938.72    68.5  922.21      88  911.14
    97.8  905.79   107.6  901.91   117.4  900.52   185.9  895.15     225  891.87
   227.4  891.81   234.8  891.62   244.6  892.11   254.3  894.89   264.1  899.49
   273.9  903.02   282.8  905.96   291.6  909.29   300.5  913.37   309.4  919.24
   318.3  925.47   327.2  931.59     336  937.48
#Mann= 3 , 0 , 0
       0      .1       0   227.4    .045       0   244.6      .1       0
Bank Sta=227.4,244.6
XS Rating Curve= 0 ,0
Exp/Cntr=0.3,0.1

Type RM Length L Ch R = 1 ,285.8   ,181.8,181,180.6
XS GIS Cut Line= 3
     1879012.722      482602.744     1879240.153      482451.703
     1879300.917      482411.772
#Sta/Elev= 20
       0  934.88    58.5  904.42    68.2  900.77      78  899.09     156     894
   185.3  892.16   214.5  890.19   222.3  889.55   224.3  889.38     234  888.86
   243.8  888.99   253.5  893.17   263.3  905.83     273  917.19   282.1   923.3
   291.2  928.76   300.3  934.08   318.5  944.53   336.6  954.82   345.7  959.89
#Mann= 3 , 0 , 0
       0      .1       0   222.3    .045       0   243.8      .1       0
Bank Sta=222.3,243.8
XS Rating Curve= 0 ,0
Exp/Cntr=0.3,0.1

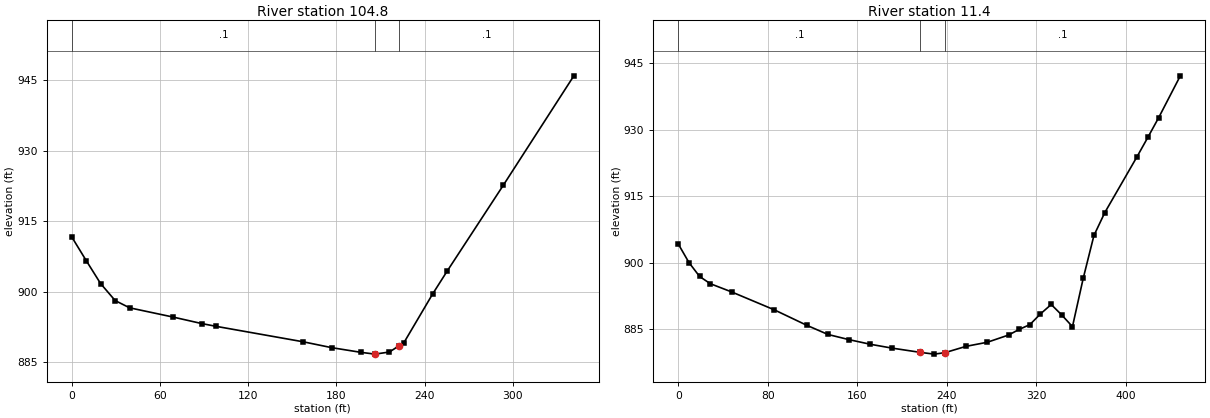
Type RM Length L Ch R = 1 ,104.8   ,91.4,93.4,95.4
XS GIS Cut Line= 4
     1879122.097      482719.064     1879273.139      482647.883
     1879337.375      482602.744     1879387.722      482521.147
#Sta/Elev= 19
       0  911.65     9.8  906.64    19.6  901.75    29.5  898.14    39.3   896.6
    68.8  894.64    88.4  893.25    98.2  892.66   157.2  889.39   176.8  888.13
   196.4  887.15   206.2  886.76     216  887.21   222.4  888.51   225.9  889.22
   245.5   899.6   255.1  904.32   293.4  922.62   341.4  945.88
#Mann= 3 , 0 , 0
       0      .1       0   206.2    .045       0   222.4      .1       0
Bank Sta=206.2,222.4
XS Rating Curve= 0 ,0
Exp/Cntr=0.3,0.1

Type RM Length L Ch R = 1 ,11.4    ,11.1,11.4,11.6
XS GIS Cut Line= 4
     1879146.403      482741.633     1879280.083      482746.842
     1879469.319      482637.467     1879491.889      482543.717
#Sta/Elev= 30
       0  904.24     9.6  900.04    19.1   896.9    28.7  895.27    47.8  893.41
      86  889.36   114.7  885.91   133.8  883.82   152.8  882.64   171.8   881.6
   190.8  880.75   216.5  879.77   228.8  879.38   238.3   879.7   257.3  881.14
   276.3  882.06   295.3  883.69   304.8  884.97   314.3  886.03   323.8  888.46
   333.4  890.58   342.8  888.22   352.4  885.58     362  896.48   371.6  906.16
   381.3  911.32   410.2  923.97   419.8   928.3   429.5  932.76   448.8  942.18
#Mann= 3 , 0 , 0
       0      .1       0   216.5    .045       0   238.3      .1       0
Bank Sta=216.5,238.3
XS Rating Curve= 0 ,0
Exp/Cntr=0.3,0.1

Chan Stop Cuts=-1
Use User Specified Reach Order=0
Composite Channel Slope=5